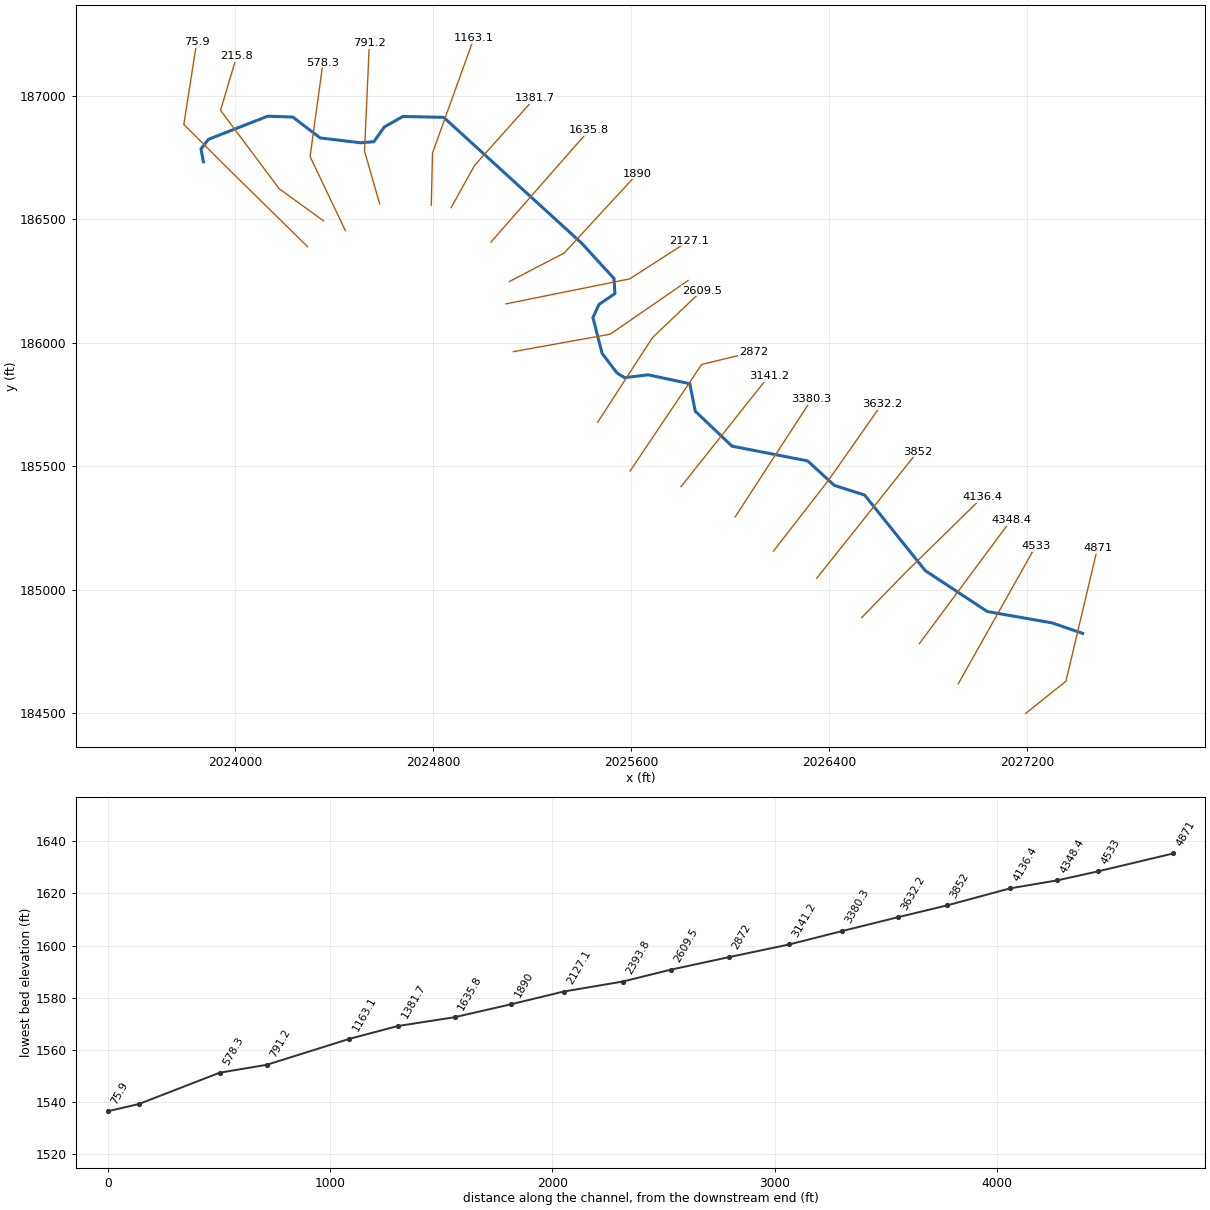
--- STNKLKCKT1.prj (project) ---

Proj Title=STNKLKCKT1
Current Plan=p01
Default Exp/Contr=0,0
English Units
Geom File=g01
Flow File=f01
Plan File=p01
BEGIN DESCRIPTION:
END DESCRIPTION:
DSS Export Rating Curves= 0
DSS Export Rating Curve Sorted= 0
DSS Export Volume Flow Curves= 0
DXF OffsetX= 0
DXF OffsetY= 0
DXF ScaleX= 0
DXF ScaleY= 0

--- STNKLKCKT1.p01 (plan) ---

Plan Title=Floodplain
Program Version=4.00
Geom File=g01
Flow File=f01
K Sum by GR=0
Std Step Tol=0.01
Critical Tol=0.01
Num of Std Step Trials=20
Max Error Tol=0.3
Flow Tol Ratio=0.001
Split Flow NTrial=30
Split Flow Tol=0.02
Split Flow Ratio=0.02
Log Output Level=0
Friction Slope Method=1
Unsteady Friction Slope Method=2
Unsteady Bridges Friction Slope Method=1
Global Log Level=0
CheckData=False
Run HTab=0
Run UNet=0
Run PostProcess=0
UNET Theta=0
UNET Theta Warmup=0
UNET ZTol=0
UNET ZSATol=0
UNET MxIter=0
UNET MaxInSteps=0
UNET DtIC=0
UNET DtMin=0
UNET MaxCRTS=0
UNET WFStab=0
UNET SFStab=0
UNET WFX=0
UNET SFX=0
UNET DSS MLevel=0
UNET DZMax Abort=0
UNET Convert EG Bridges=0
UNET Use Existing IB Tables=0
UNET Froude Limit=0
UNET Froude Power=0
Write IC File=0
Echo Input=False
Echo Output=False
Write Detailed=0

--- STNKLKCKT1.f01 (steady flow) ---

Flow Title=NFF Regression Equation
Program Version=4.00
Number of Profiles=1
Profile Names=P100yr
River Rch & RM=STNKLKCKT1,Main      ,4871
421.7839
River Rch & RM=STNKLKCKT1,Main      ,4533
543.2327
River Rch & RM=STNKLKCKT1,Main      ,3141.2
554.6356
River Rch & RM=STNKLKCKT1,Main      ,2393.8
614.6488
River Rch & RM=STNKLKCKT1,Main      ,578.3
639.6771
River Rch & RM=STNKLKCKT1,Main      ,215.8
641.5056
Boundary for River Rch & Prof#=STNKLKCKT1,Main      ,1
Up Type=0
Dn Type=3
Dn Slope=0.023142

--- STNKLKCKT1.g01 (geometry) ---

Geom Title=USGS 10m DEM
Program Version=4.10

River Reach=STNKLKCKT1      ,Main
Reach XY= 30
     2027426.065      184823.849     2027302.252      184866.357
     2027040.422      184912.267     2026789.554      185078.066
     2026544.441      185383.991     2026421.932      185423.118
     2026314.164      185522.227     2026008.304      185581.972
     2025859.866      185723.465     2025837.775      185834.727
     2025669.094      185870.797     2025573.837      185859.104
      2025542.94      185878.998      2025483.33      185957.255
     2025446.238      186102.371     2025470.743      186155.692
     2025535.066      186199.616     2025531.594       186260.38
     2025401.091      186403.315     2024842.762      186913.276
     2024677.832      186916.531     2024602.962      186874.214
     2024560.644      186814.535     2024506.391      186810.194
      2024343.63      186829.726     2024232.953      186914.361
     2024130.957      186917.616     2023892.241        186824.3
     2023861.859      186785.238     2023871.625      186733.154

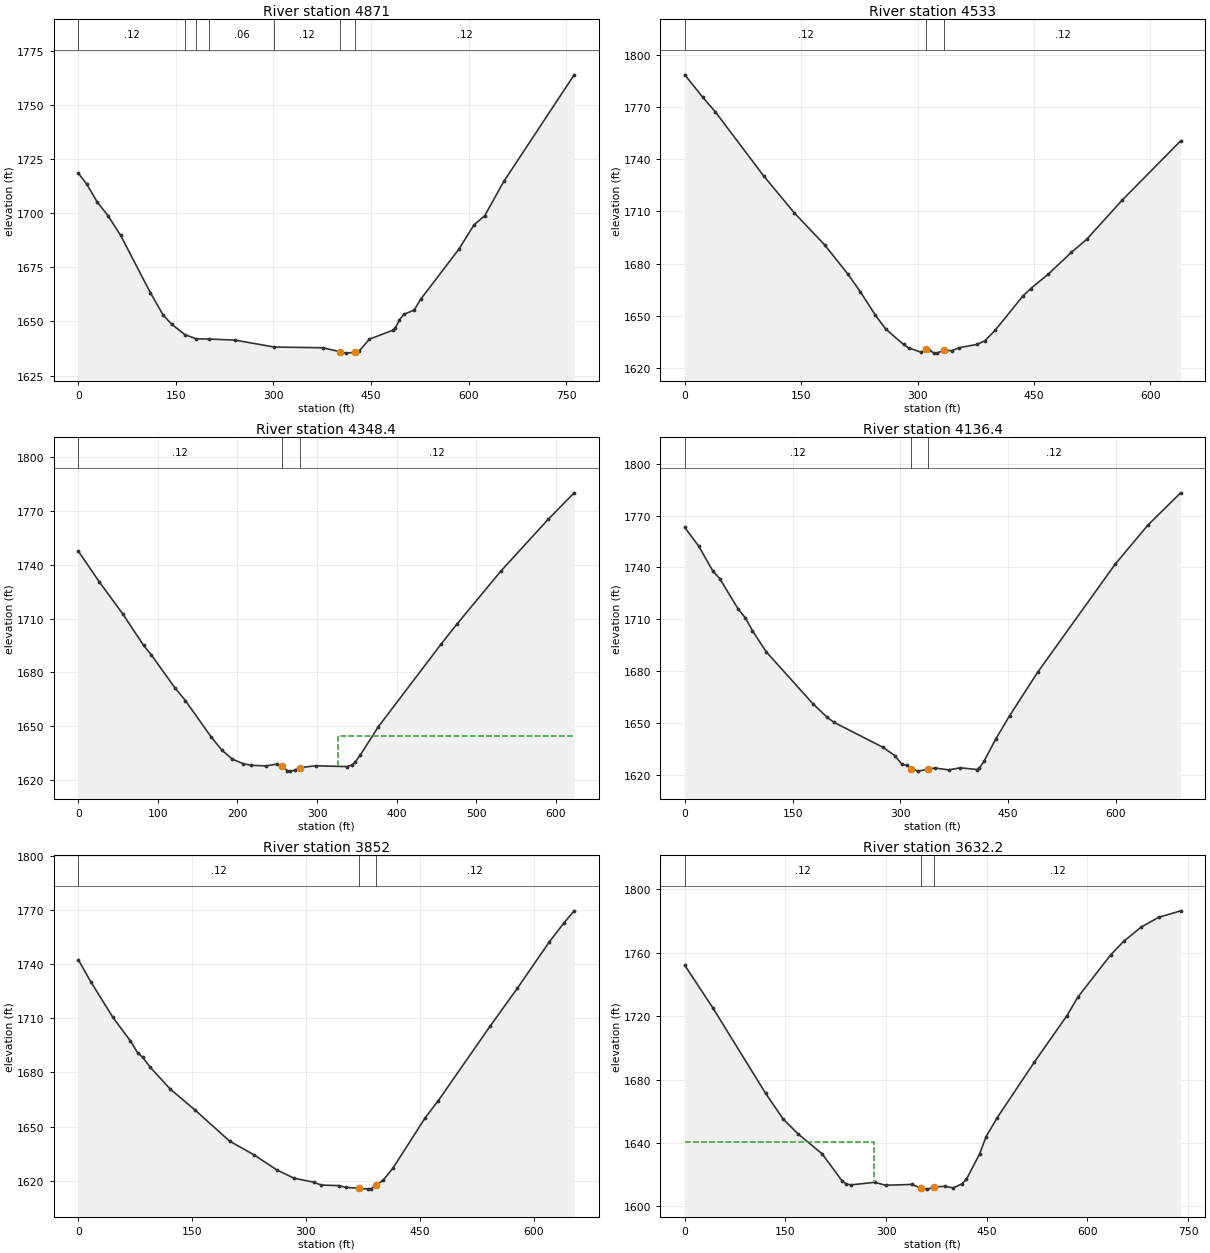
Type RM Length L Ch R = 1 ,4871    ,343.3,338,330.7
XS GIS Cut Line= 3
     2027195.623      184499.966     2027358.383      184630.175
     2027485.987      185169.237
#Sta/Elev= 30
       0 1718.52      13 1713.42    29.3 1705.05    45.6 1698.87    65.1 1689.73
   110.7 1663.32   130.3 1653.01   143.3  1648.8  163.731643.917  181.371641.968
  200.921641.869   241.2 1641.37   301.31638.173   375.6 1637.84   401.8 1636.07
   411.7 1635.36   424.8 1635.75   431.3 1636.19   447.7 1641.82   483.8 1645.96
     487 1646.78   493.6  1650.6   500.2 1653.24   516.6 1655.31   526.4 1660.26
   585.4 1683.52   608.3  1694.6   624.7 1698.78   654.2 1714.69   762.4 1763.96
#Mann= 7 ,-1 , 0
       0     .12       0  163.73     .06       0  181.37     .12       0
  200.92     .06       0   301.3     .12       0   401.8    .045       0
   424.8     .12       0
Bank Sta=401.8,424.8
XS Rating Curve= 0 ,0
Exp/Cntr=0.3,0.1

Type RM Length L Ch R = 1 ,4533    ,187.5,184.6,181.8
XS GIS Cut Line= 2
     2026923.081      184619.742     2027235.987       185177.05
#Sta/Elev= 30
       0 1788.58    22.9 1775.82    39.3 1767.33   101.6 1730.49   140.9 1709.31
   180.3 1690.76   209.8 1674.22   226.2 1663.85   245.8 1650.26   258.9 1642.42
   281.9 1633.51   288.4 1631.53   304.8 1629.02   311.4 1630.76   314.6 1630.58
   321.2 1628.51   324.5 1628.53   334.3 1630.11   344.2 1629.94     354 1631.68
   376.9 1633.56   386.8 1635.64   399.9 1641.57   435.9 1661.44   445.8 1665.62
   468.7 1674.02   498.2 1686.42   517.9 1693.91   563.8 1716.52   639.1  1750.6
#Mann= 3 ,-1 , 0
       0     .12       0   311.4    .045       0   334.3     .12       0
Bank Sta=311.4,334.3
XS Rating Curve= 0 ,0
Exp/Cntr=0.3,0.1

Type RM Length L Ch R = 1 ,4348.4  ,215.2,212,208.4
XS GIS Cut Line= 2
     2026765.935      184782.518     2027136.922      185283.133
#Sta/Elev= 30
       0 1747.64    26.2 1730.59    55.8 1712.67      82 1695.11    91.8 1689.76
   121.3  1671.5   134.5 1664.38   167.2 1643.91   180.4 1636.74   193.5 1631.75
   206.6 1629.26   216.4 1628.31   236.1 1627.93   249.2 1628.96   255.8 1627.86
   262.4 1625.36   265.6 1625.03   272.2 1625.53   278.8 1627.01   298.4    1628
   337.8 1627.56   344.3 1628.58   347.6 1629.95   354.2 1633.91   377.1 1649.83
   455.8 1695.76   475.5 1706.82   531.3 1736.65   590.3 1765.28   623.1 1780.11
#Mann= 3 ,-1 , 0
       0     .12       0   255.8    .045       0   278.8     .12       0
#XS Ineff= 2 , 0
                          326.85         1644.43
Permanent Ineff=
       F       F
Bank Sta=255.8,278.8
XS Rating Curve= 0 ,0
Exp/Cntr=0.3,0.1

Type RM Length L Ch R = 1 ,4136.4  ,281.5,284.4,287.1
XS GIS Cut Line= 3
     2026532.862      184887.987     2026713.852      185074.185
     2027021.161      185375.426
#Sta/Elev= 30
       0 1763.15    19.5 1752.26      39 1737.91    48.7  1733.5    74.6 1715.68
    84.4  1710.8    94.1 1703.34   113.6 1690.97   178.5 1660.92     198 1653.18
   207.7 1650.22     276 1635.71   292.3 1630.92     302    1626   308.6 1625.32
   315.3 1623.46   324.9 1621.97   337.9 1623.04   347.7 1623.78   367.2 1622.72
   383.6  1623.9   406.4  1622.9   409.6 1623.56   416.2 1627.55   432.4 1640.34
     452 1654.06   491.1  1679.3   598.7 1741.77   644.4 1764.51     690 1783.23
#Mann= 3 ,-1 , 0
       0     .12       0   315.3    .045       0   337.9     .12       0
Bank Sta=315.3,337.9
XS Rating Curve= 0 ,0
Exp/Cntr=0.3,0.1

Type RM Length L Ch R = 1 ,3852    ,218.9,219.8,220.7
XS GIS Cut Line= 2
     2026351.076      185047.314     2026758.123       185558.56
#Sta/Elev= 30
       0 1742.32    16.3 1730.24    45.7 1710.38    68.6 1697.43    78.4 1690.76
      85  1688.3    94.8 1682.82   120.9 1670.88   153.6 1659.27   199.3 1642.03
     232 1634.26   261.4 1626.11   284.3 1621.48   310.4 1619.24   320.2 1617.67
   343.1 1617.37   352.9 1616.35   370.4 1615.93   382.3 1615.42   385.4 1615.51
   392.1 1617.53   401.9 1620.34     415 1627.26   457.4 1655.04   473.8 1664.02
   542.4  1705.4   578.4 1726.43   620.8 1752.23   640.4 1762.91   653.5  1769.4
#Mann= 3 ,-1 , 0
       0     .12       0   370.4    .045       0   392.1     .12       0
Bank Sta=370.4,392.1
XS Rating Curve= 0 ,0
Exp/Cntr=0.3,0.1

Type RM Length L Ch R = 1 ,3632.2  ,249.4,252,251.4
XS GIS Cut Line= 3
     2026176.059      185156.726     2026399.128      185444.708
     2026613.815      185751.664
#Sta/Elev= 30
       0 1752.14    42.3 1724.93   120.3 1671.45   146.4 1655.23   169.1 1645.64
   204.9 1633.08   234.2  1616.2   240.7 1614.19   247.2  1613.6     283 1615.21
   299.2 1613.37   338.2 1613.88   351.3 1611.63     361 1610.92   371.8  1612.2
   387.1 1612.72   400.1 1611.76   413.1 1614.26   419.6 1617.15   439.2 1633.06
     449 1644.06   465.2 1655.81   520.6  1690.9   569.5 1720.42   585.8 1732.13
   634.6 1758.72   654.2 1767.32   680.2 1776.29   706.3 1782.44   738.8 1786.49
#Mann= 3 ,-1 , 0
       0     .12       0   351.3    .045       0   371.8     .12       0
#XS Ineff= 2 , 0
          281.74 1640.48
Permanent Ineff=
       F       F
Bank Sta=351.3,371.8
XS Rating Curve= 0 ,0
Exp/Cntr=0.3,0.1

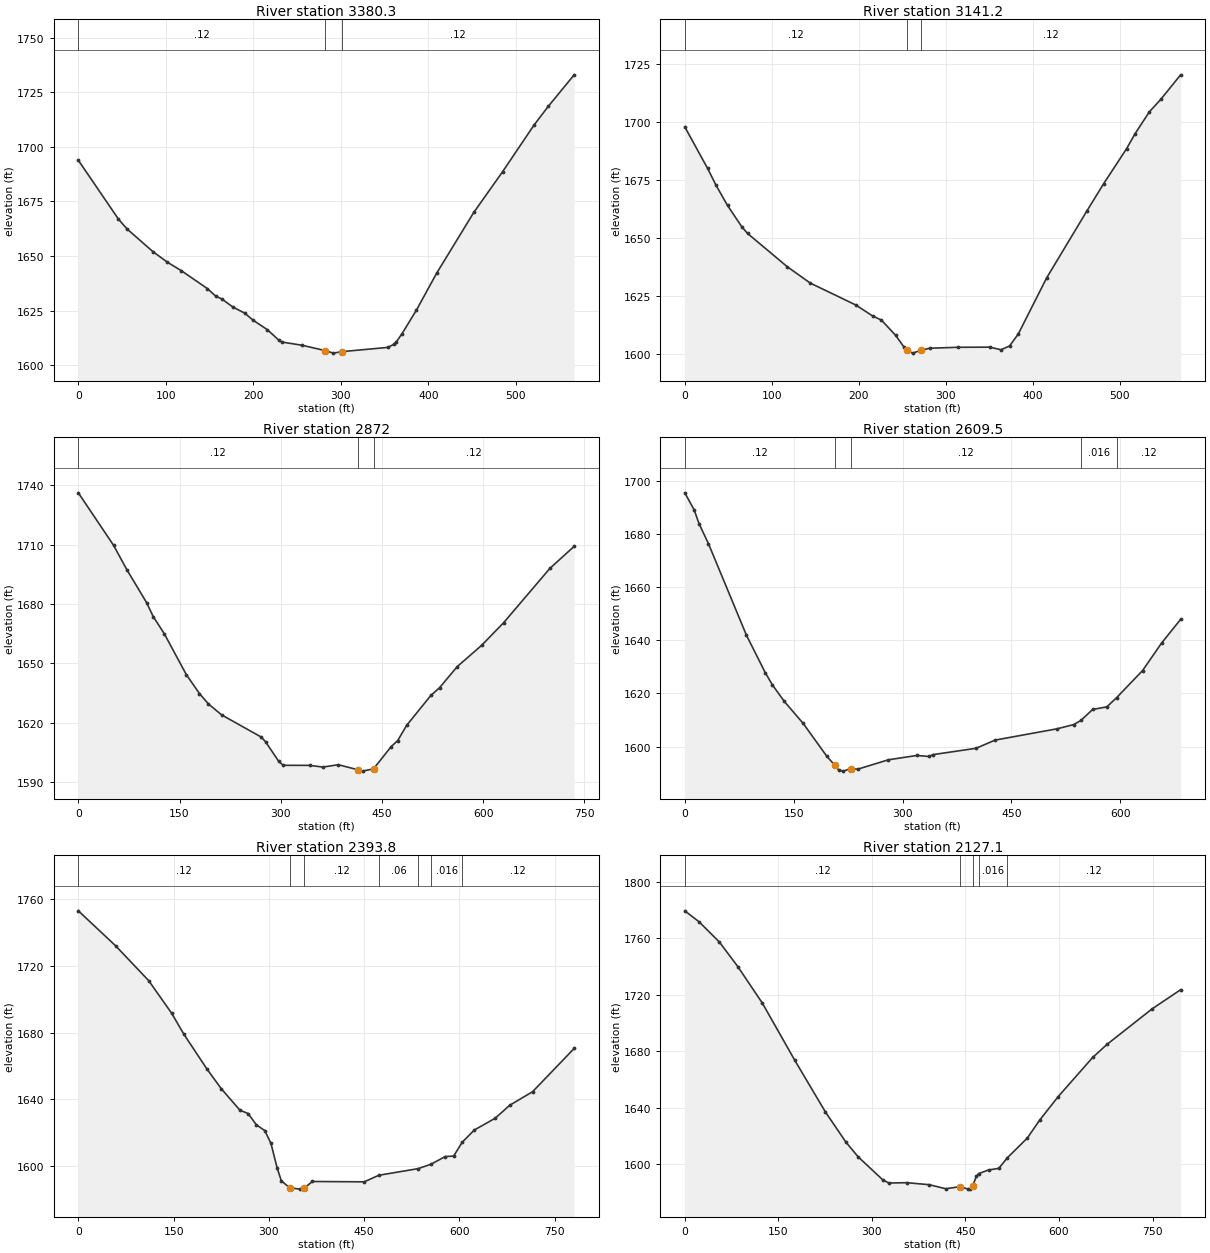
Type RM Length L Ch R = 1 ,3380.3  ,240.8,239.1,237
XS GIS Cut Line= 2
     2026021.143      185295.539     2026329.737        185770.8
#Sta/Elev= 30
       0 1693.87    45.9  1666.9    55.7 1662.42    85.2 1652.07   101.5 1647.29
   117.9 1643.28   147.4 1635.16   157.2 1631.62   163.8 1630.43   176.9 1626.62
     190 1623.93   199.8 1620.66   216.2 1616.28   229.3 1611.46   232.6 1610.67
   255.5 1609.21   281.7 1606.79   291.5 1605.59   301.1 1606.27   353.8 1608.21
   360.3 1609.56   363.6 1610.83   370.1 1614.57   386.5 1625.33   409.4 1642.08
     452 1670.01   484.8 1688.57   520.8 1709.97   537.2 1718.59   566.7 1732.98
#Mann= 3 ,-1 , 0
       0     .12       0   281.7    .045       0   301.1     .12       0
Bank Sta=281.7,301.1
XS Rating Curve= 0 ,0
Exp/Cntr=0.3,0.1

Type RM Length L Ch R = 1 ,3141.2  ,265.2,269.2,270.2
XS GIS Cut Line= 2
     2025802.393      185417.935      2026156.56       185864.55
#Sta/Elev= 30
       0 1697.94    26.2 1680.05      36 1672.73    49.1 1664.09    65.5 1654.91
    72.1 1652.04   117.9 1637.65   144.1 1630.66   196.6 1621.18   216.2 1616.39
     226  1614.7   242.4 1608.09   252.2 1602.94   255.5 1601.66   262.1 1600.44
   271.3 1601.67   281.7 1602.56   314.5 1602.96   350.5 1603.02   363.6 1601.89
   373.4 1603.55   383.3 1608.64     416 1632.88   461.9  1661.5   481.6 1673.51
   507.8 1688.51   517.6 1694.98     534 1704.41   547.1 1709.77     570 1720.38
#Mann= 3 ,-1 , 0
       0     .12       0   255.5    .045       0   271.3     .12       0
Bank Sta=255.5,271.3
XS Rating Curve= 0 ,0
Exp/Cntr=0.3,0.1

Type RM Length L Ch R = 1 ,2872    ,261.5,262.5,259.2
XS GIS Cut Line= 3
     2025596.725      185481.322     2025885.727      185912.727
     2026095.362      185963.508
#Sta/Elev= 30
       0 1736.14    52.2 1709.66    71.8  1697.4   101.2 1680.69     111 1673.67
   127.4    1665     160 1644.39   179.6 1634.75   192.7  1629.6   212.3 1624.03
   271.1 1612.83   277.6  1610.4   297.2 1600.48   303.7 1598.55   342.9 1598.52
   362.5 1597.66   385.4 1598.85   414.8 1596.27   421.3 1595.61   437.6 1596.77
   463.7 1607.98   473.5 1611.07   486.6 1618.68   522.5  1633.8   535.6 1637.78
   561.8 1648.44   597.7 1659.08   630.4 1670.54     699 1697.98     735 1709.12
#Mann= 3 ,-1 , 0
       0     .12       0   414.8    .045       0   437.6     .12       0
Bank Sta=414.8,437.6
XS Rating Curve= 0 ,0
Exp/Cntr=0.3,0.1

Type RM Length L Ch R = 1 ,2609.5  ,233.4,215.8,197.4
XS GIS Cut Line= 3
     2025465.154      185678.352     2025686.508        186020.8
     2025885.727      186210.904
#Sta/Elev= 30
       0 1695.41      13 1688.95    19.6 1683.82    32.6  1676.3    84.8 1641.97
   110.9 1627.79   120.7 1623.21     137 1617.04   163.1 1608.73   195.7 1596.37
   206.8 1592.98     212 1591.21   218.6  1590.8   228.4 1591.77   238.1 1591.52
   280.5 1595.06   319.7 1596.69     336 1596.32   342.5 1597.03   401.2 1599.38
   427.4 1602.46   512.7  1606.7   535.6 1608.28   545.81609.848   561.8 1613.97
   581.5 1614.96  595.081618.461   630.7 1628.61   656.9 1638.96   683.1 1647.85
#Mann= 5 ,-1 , 0
       0     .12       0   206.8    .045       0   228.4     .12       0
   545.8    .016       0  595.08     .12       0
Bank Sta=206.8,228.4
XS Rating Curve= 0 ,0
Exp/Cntr=0.3,0.1

Type RM Length L Ch R = 1 ,2393.8  ,264.8,266.7,265.9
XS GIS Cut Line= 3
      2025124.41      185964.463     2025515.935      186035.123
     2025831.039       186252.57
#Sta/Elev= 30
       0 1752.88    58.7 1731.95   110.9 1711.03   146.8 1691.63   166.3 1678.93
   202.2 1658.33     225 1646.41   254.4 1633.54   267.4 1631.49   280.4 1624.75
   293.5 1621.32   303.3 1613.64   313.1 1598.85   319.6 1591.26   332.6 1587.07
   348.9 1586.25   355.5 1586.75   368.5 1590.82   450.2 1590.62  473.231594.556
   535.11598.523  555.471601.199   577.8 1605.77   590.9 1606.03  604.55 1614.37
   623.6 1621.68   656.4 1628.71   679.3 1636.48   715.3  1644.6   780.7 1670.48
#Mann= 7 ,-1 , 0
       0     .12       0   332.6    .045       0   355.5     .12       0
  473.23     .06       0   535.1     .12       0  555.47    .016       0
  604.55     .12       0
Bank Sta=332.6,355.5
XS Rating Curve= 0 ,0
Exp/Cntr=0.3,0.1

Type RM Length L Ch R = 1 ,2127.1  ,220.8,237.1,250.3
XS GIS Cut Line= 3
      2025095.11       186158.09     2025594.928      186259.081
     2025834.511      186413.595
#Sta/Elev= 30
       0  1779.5    22.9 1771.74    55.6 1757.32      85 1740.02   124.2 1714.24
   176.5 1673.53   225.5 1637.03   258.2 1615.78   277.8 1605.34   317.1 1589.12
   326.9 1586.74   356.3 1586.96   392.2 1585.52   418.4 1582.66   441.3 1584.14
   454.4  1582.4   457.6 1582.44  461.79 1584.95   467.4 1591.37  471.081593.354
     487 1595.98   503.4 1597.08  516.821604.436   549.2 1618.58   568.9 1631.22
   598.4 1647.78   654.1 1675.72     677 1684.92   749.1 1710.01     795 1723.63
#Mann= 5 ,-1 , 0
       0     .12       0   441.3    .045       0  461.79     .12       0
  471.08    .016       0  516.82     .12       0
Bank Sta=441.3,461.79
XS Rating Curve= 0 ,0
Exp/Cntr=0.3,0.1

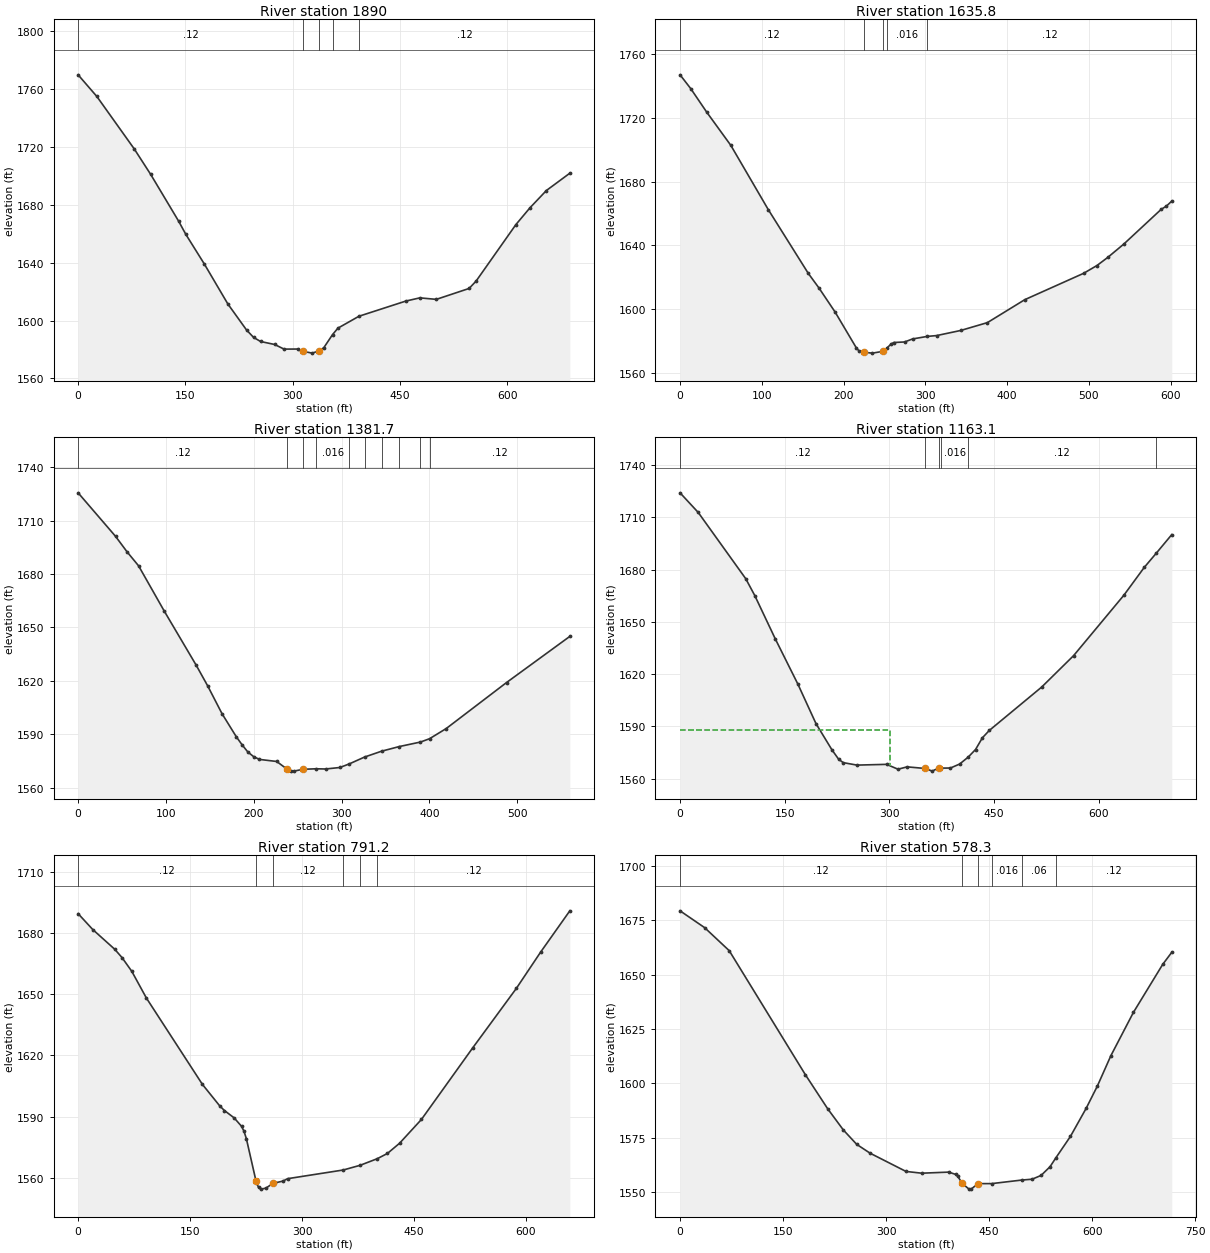
Type RM Length L Ch R = 1 ,1890    ,253.5,254.2,254.6
XS GIS Cut Line= 3
     2025108.817      186248.664     2025329.303      186363.248
     2025626.664      186685.744
#Sta/Elev= 30
       0 1769.92    26.2 1754.94    78.5 1718.65   101.4 1701.09   140.6 1668.64
   150.4 1659.73   176.6 1638.96   209.2 1611.56   235.4  1593.5   245.2 1588.41
     255 1585.56   274.7 1583.49   287.8  1580.3   307.4 1580.35     314 1578.83
     327 1577.52   336.9 1579.08   343.4  1581.3  355.571590.323   363.1 1594.79
  392.521603.024     458 1613.51   477.6 1615.73   500.6 1614.69   546.4 1622.23
   556.2 1627.32   611.8 1666.37   631.5    1678   654.4 1689.93   687.2 1701.91
#Mann= 5 ,-1 , 0
       0     .12       0     314    .045       0   336.9     .12       0
  355.57    .016       0  392.52     .12       0
Bank Sta=314,336.9
XS Rating Curve= 0 ,0
Exp/Cntr=0.3,0.1

Type RM Length L Ch R = 1 ,1635.8  ,254.3,254.1,253.8
XS GIS Cut Line= 2
     2025034.164      186408.386       2025430.3      186860.915
#Sta/Elev= 30
       0 1746.81    13.1 1738.16    32.7 1723.38    62.1 1702.64   107.9 1662.42
   156.9 1622.44     170 1613.27   189.6 1598.31   215.7 1575.76     219 1573.87
   225.5 1573.02   235.3 1572.55   248.4 1573.69  253.041575.749   258.2 1578.28
   261.5  1579.2   274.6 1579.54   284.4 1581.43   302.41583.016   313.8 1583.54
   343.2 1586.73   375.9 1591.65   421.6 1606.01   493.6 1622.52   509.9  1627.4
     523 1632.43   542.6 1640.77   588.4 1662.55   594.9 1664.63   601.4 1667.73
#Mann= 5 ,-1 , 0
       0     .12       0   225.5    .045       0   248.4     .12       0
  253.04    .016       0   302.4     .12       0
Bank Sta=225.5,248.4
XS Rating Curve= 0 ,0
Exp/Cntr=0.3,0.1

Type RM Length L Ch R = 1 ,1381.7  ,209.8,218.6,227.2
XS GIS Cut Line= 3
     2024872.706      186547.275     2024968.192       186719.15
     2025210.125      186989.971
#Sta/Elev= 30
       0 1725.58    42.6 1701.13    55.7 1692.43    68.8 1684.58    98.3 1658.92
   134.4 1628.74   147.5  1617.1   163.8  1601.5   180.2 1588.42   186.8 1583.91
   193.3 1579.91   199.9 1577.32   206.4 1575.79   226.1 1574.62  237.52 1570.45
   242.4 1569.22   245.7  1569.2     256 1570.23  270.98 1570.52   281.7  1570.4
     298 1571.24  308.721573.265  326.141577.116  345.451580.395  365.75 1583.02
  389.791585.547  400.071587.404   419.1 1593.14   487.8    1619   559.8 1644.91
#Mann= 10 ,-1 , 0
       0     .12       0  237.52    .045       0     256     .12       0
  270.98    .016       0  308.72     .06       0  326.14     .12       0
  345.45    .016       0  365.75     .06       0  389.79    .016       0
  400.07     .12       0
Bank Sta=237.52,256
XS Rating Curve= 0 ,0
Exp/Cntr=0.3,0.1

Type RM Length L Ch R = 1 ,1163.1  ,365.3,371.9,378.3
XS GIS Cut Line= 3
     2024792.845      186557.692     2024797.619       186768.63
      2024964.72      187233.039
#Sta/Elev= 30
       0 1724.08      26 1712.83    94.1 1674.79   107.1 1665.08   136.3 1640.35
   168.8 1614.27   194.8 1591.55   217.5  1576.6   227.3 1571.07   233.9 1569.14
   253.5 1567.73     296 1568.16   312.3 1565.37   325.4 1566.72   351.5 1565.79
   361.4 1564.27   371.2 1566.26  373.951565.994   387.5 1566.06   400.6 1568.33
  412.771572.276   423.4 1576.67   433.3 1583.43   443.1 1587.62   518.2 1612.54
     564 1630.61   635.9 1665.24   665.3 1681.31  682.331689.373   704.6 1700.08
#Mann= 6 ,-1 , 0
       0     .12       0   351.5    .045       0   371.2     .12       0
  373.95    .016       0  412.77     .12       0  682.33    .016       0
#XS Ineff= 2 , 0
          300.73 1588.07
Permanent Ineff=
       F       F
Bank Sta=351.5,371.2
XS Rating Curve= 0 ,0
Exp/Cntr=0.3,0.1

Type RM Length L Ch R = 1 ,791.2   ,214.6,212.9,211.2
XS GIS Cut Line= 3
     2024584.077        186562.9     2024522.879      186776.442
     2024542.411       187212.64
#Sta/Elev= 30
       0 1689.68    19.6 1681.88      49  1672.2    58.8  1668.1    71.9 1661.34
    91.5  1648.2   166.6 1605.75   189.5 1595.32     196 1592.95   209.1 1589.31
   218.9 1585.21   222.1  1582.9   225.4 1579.14   238.4 1558.21   241.7 1555.14
     245 1554.32   251.5 1554.79   261.2 1557.19   274.3 1558.25   280.8 1559.46
  355.271563.723  377.831566.028  400.891569.288   414.4 1571.85   430.7 1576.87
     460 1588.57   528.4 1623.59   587.1 1652.93   619.7  1670.8   658.8 1691.07
#Mann= 6 ,-1 , 0
       0     .12       0   238.4    .045       0   261.2     .12       0
  355.27    .016       0  377.83     .06       0  400.89     .12       0
Bank Sta=238.4,261.2
XS Rating Curve= 0 ,0
Exp/Cntr=0.3,0.1

Type RM Length L Ch R = 1 ,578.3   ,344.7,362.6,379.2
XS GIS Cut Line= 3
     2024445.532      186454.316     2024302.827      186754.307
     2024354.911      187134.515
#Sta/Elev= 30
       0  1679.3    35.8 1671.56    71.6 1660.97   182.4 1603.95     215 1588.23
   237.8 1578.48   257.3 1571.85   276.8 1567.79     329 1559.41   351.9  1558.6
   391.2  1559.1   401.1 1558.07   404.4 1557.18   410.9 1553.89   420.8 1551.27
     424 1551.31   433.9  1553.8  453.821553.811  497.391555.439   512.6 1555.83
   525.7 1557.57   538.8 1561.59  547.23 1565.66   568.4 1575.49   591.3 1588.41
   607.7  1598.7   627.4 1612.69   660.2 1632.59   702.8 1654.65     716 1660.21
#Mann= 6 ,-1 , 0
       0     .12       0   410.9    .045       0   433.9     .12       0
  453.82    .016       0  497.39     .06       0  547.23     .12       0
Bank Sta=410.9,433.9
XS Rating Curve= 0 ,0
Exp/Cntr=0.3,0.1

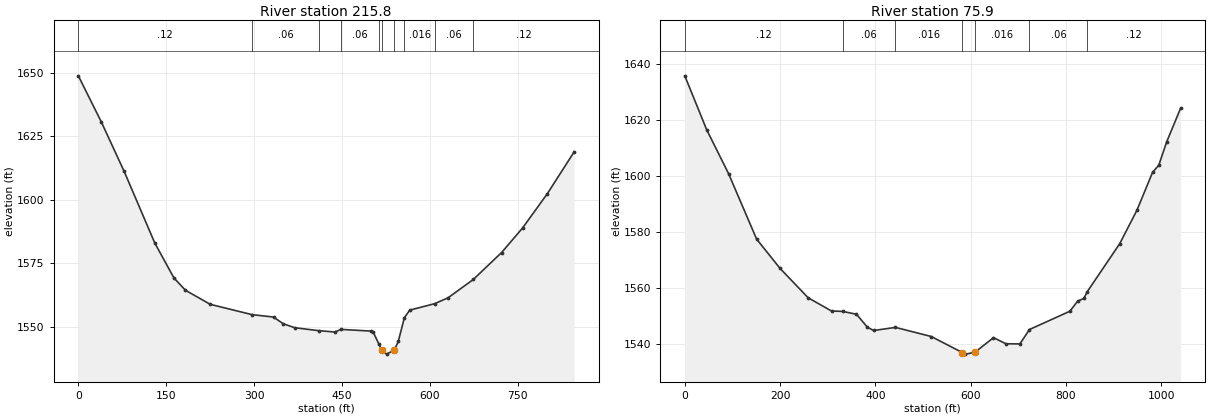
Type RM Length L Ch R = 1 ,215.8   ,137.3,139.9,143.3
XS GIS Cut Line= 4
     2024357.515       186493.89     2024177.827      186624.098
     2023940.848      186941.807     2024005.952      187160.557
#Sta/Elev= 30
       0 1648.89    39.2 1630.75    78.3 1611.22   130.5 1583.06   163.2 1569.29
   182.8 1564.45   225.2 1558.89  296.641554.827   333.3 1553.88   349.7 1551.25
   369.3 1549.69  410.471548.515   438.1 1547.99  448.381549.025   500.3 1548.34
   503.6 1547.88  512.741543.435  518.26 1540.73   526.5 1539.28   539.6 1540.91
   546.2 1544.26   556.7 1553.65   565.8 1556.61  608.351559.147   631.3 1561.48
  674.261568.675   722.6 1579.29   758.5 1588.98   800.8  1602.5   846.5 1618.95
#Mann= 10 ,-1 , 0
       0     .12       0  296.64     .06       0  410.47    .016       0
  448.38     .06       0  512.74     .12       0  518.26    .045       0
   539.6     .12       0   556.7    .016       0  608.35     .06       0
  674.26     .12       0
Bank Sta=518.26,539.6
XS Rating Curve= 0 ,0
Exp/Cntr=0.3,0.1

Type RM Length L Ch R = 1 ,75.9    ,53.3,75.9,98.3
XS GIS Cut Line= 4
     2024292.411      186389.723     2023974.702      186702.223
     2023792.411      186884.515     2023844.494      187217.848
#Sta/Elev= 30
       0 1635.91    45.9 1616.67    91.8    1601   150.7 1577.61   199.9 1567.14
   258.9 1556.64     308 1551.91  331.461551.774   360.4 1550.74   383.4  1546.1
   396.5 1544.95  442.271546.055   517.4  1542.8   582.7 1537.06   589.2 1536.51
   608.8 1537.14     648  1542.4   674.1  1540.2   703.4 1540.16  723.481545.304
   808.3 1551.82   824.6 1555.42   837.7 1556.41  844.841558.811   913.1    1576
   949.1  1587.9   981.9 1601.44     995    1604  1011.3 1612.23  1040.8 1624.36
#Mann= 7 ,-1 , 0
       0     .12       0  331.46     .06       0  442.27    .016       0
   582.7    .045       0   608.8    .016       0  723.48     .06       0
  844.84     .12       0
Bank Sta=582.7,608.8
XS Rating Curve= 0 ,0
Exp/Cntr=0.3,0.1

Chan Stop Cuts=-1
Use User Specified Reach Order=0
Composite Channel Slope=5